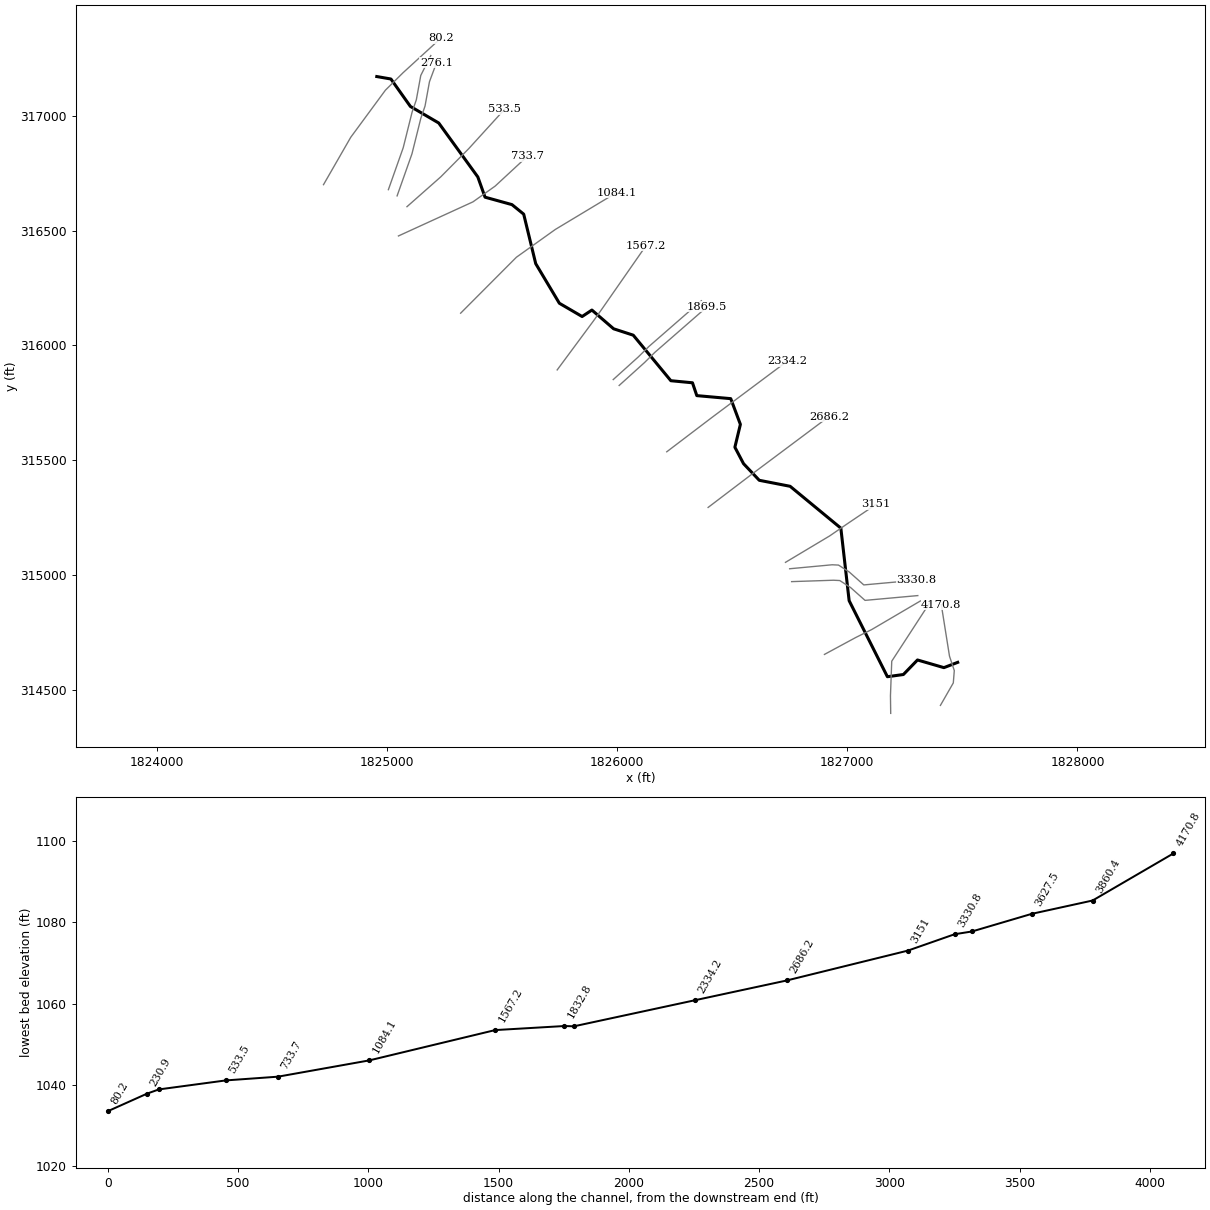
--- DogRun.prj (project) ---

Proj Title=DogRun
Current Plan=p01
Default Exp/Contr=0,0
English Units
Geom File=g01
Flow File=f01
Plan File=p01
BEGIN DESCRIPTION:
END DESCRIPTION:
DSS Export Rating Curves= 0
DSS Export Rating Curve Sorted= 0
DSS Export Volume Flow Curves= 0
DXF OffsetX= 0
DXF OffsetY= 0
DXF ScaleX= 0
DXF ScaleY= 0

--- DogRun.p01 (plan) ---

Plan Title=Floodplain
Program Version=4.00
Geom File=g01
Flow File=f01
K Sum by GR=0
Std Step Tol=0.01
Critical Tol=0.01
Num of Std Step Trials=20
Max Error Tol=0.3
Flow Tol Ratio=0.001
Split Flow NTrial=30
Split Flow Tol=0.02
Split Flow Ratio=0.02
Log Output Level=0
Friction Slope Method=1
Unsteady Friction Slope Method=2
Unsteady Bridges Friction Slope Method=1
Global Log Level=0
CheckData=False
Run HTab=0
Run UNet=0
Run PostProcess=0
UNET Theta=0
UNET Theta Warmup=0
UNET ZTol=0
UNET ZSATol=0
UNET MxIter=0
UNET MaxInSteps=0
UNET DtIC=0
UNET DtMin=0
UNET MaxCRTS=0
UNET WFStab=0
UNET SFStab=0
UNET WFX=0
UNET SFX=0
UNET DSS MLevel=0
UNET DZMax Abort=0
UNET Convert EG Bridges=0
UNET Use Existing IB Tables=0
UNET Froude Limit=0
UNET Froude Power=0
Write IC File=0
Echo Input=False
Echo Output=False
Write Detailed=0

--- DogRun.f01 (steady flow) ---

Flow Title=NFF Regression Equation
Program Version=4.10
Number of Profiles= 1
Profile Names=P100yr
River Rch & RM=DogRun,Main            ,4170.8
     593
River Rch & RM=DogRun,Main            ,1084.1
     655
River Rch & RM=DogRun,Main            ,276.1
     709
Boundary for River Rch & Prof#=DogRun,Main            , 1
Up Type= 0
Dn Type= 3
Dn Slope=0.02874
DSS Import GetInterval= 0
DSS Import GetPeak= 0
DSS Import FillOption= 0

--- DogRun.g01 (geometry) ---

Geom Title=USGS 10m DEM
Program Version=4.10

River Reach=DogRun          ,Main
Reach XY= 30
     1827479.799        314620.5     1827419.898      314597.454
     1827305.121      314630.829      1827243.86      314567.517
     1827174.421      314557.951     1827008.213      314888.971
     1826972.227      315204.628     1826751.912      315386.772
     1826617.911      315412.919     1826549.506      315485.317
     1826511.933      315556.871     1826535.855      315656.269
     1826494.007      315768.308     1826346.594      315781.483
      1826327.73      315837.386     1826233.857       315846.37
     1826070.552      316044.556      1825985.24      316072.367
     1825890.925      316153.939     1825848.393       316125.78
     1825749.558      316183.508     1825646.857      316355.942
     1825594.662      316571.311     1825543.749      316612.815
     1825426.767      316645.228      1825395.39      316733.301
     1825225.557      316968.144     1825102.455      317040.253
     1825017.938      317159.638     1824956.527      317170.345

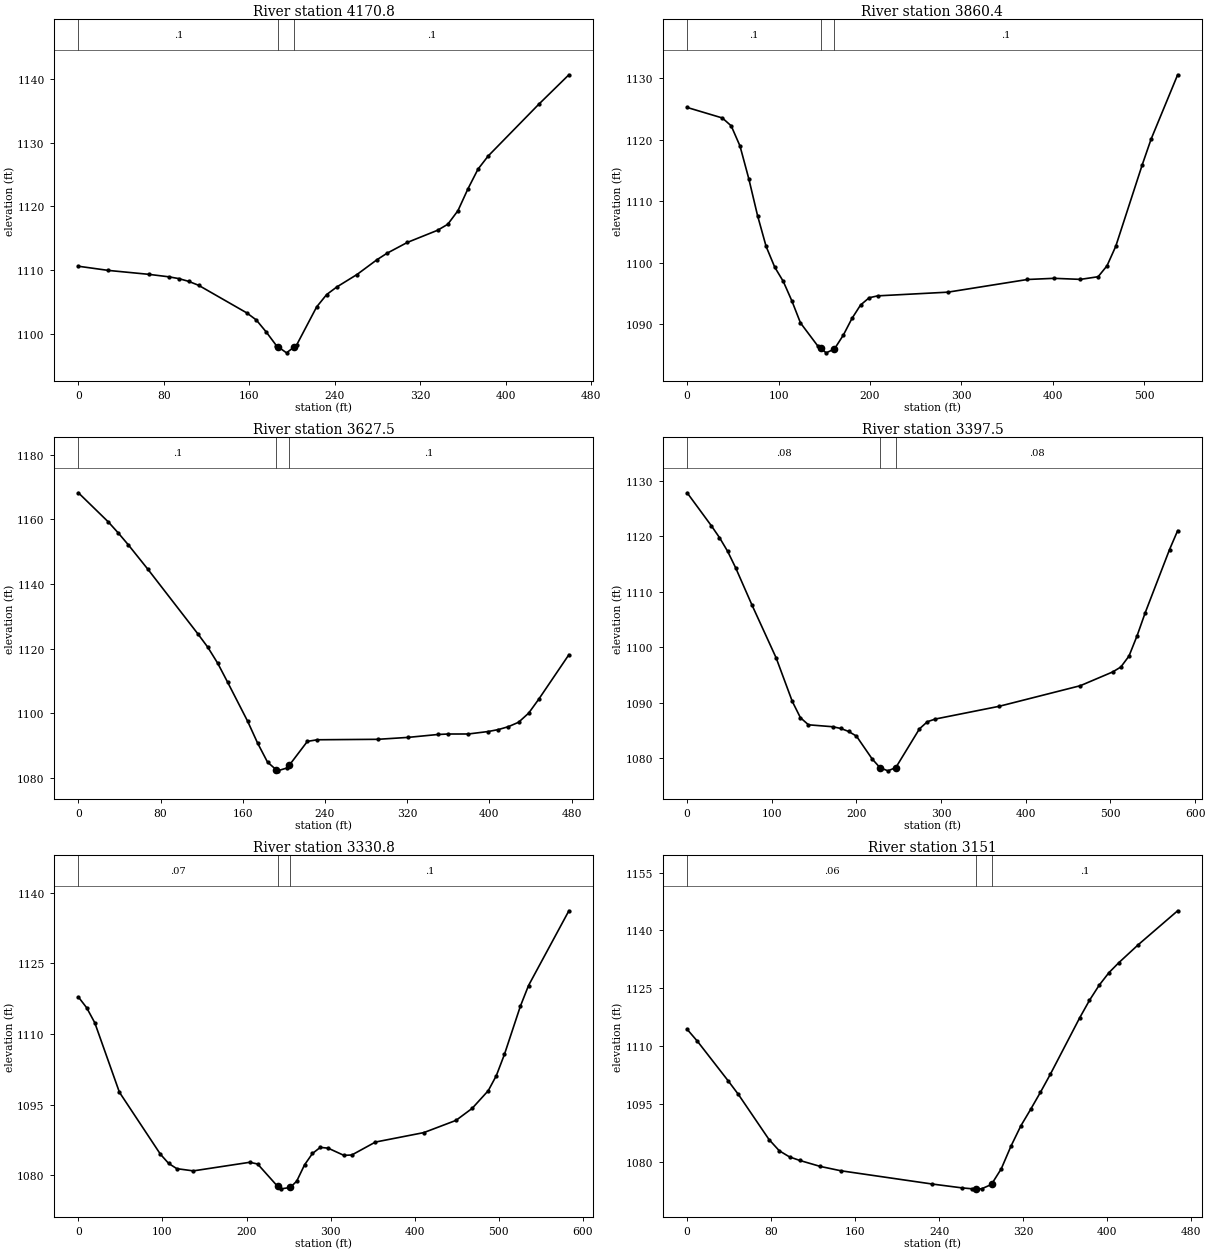
Type RM Length L Ch R = 1 ,4170.8  ,318.1,310.4,302.4
XS GIS Cut Line= 5
     1827404.708      314433.112     1827460.661      314530.876
     1827465.001      314584.696     1827444.168      314647.196
     1827408.578      314871.154
#Sta/Elev= 30
       0 1110.58    28.2 1109.92    65.7 1109.31    84.5 1108.92    93.9 1108.64
   103.3  1108.2   112.6 1107.58   157.6 1103.25   166.6 1102.13     176 1100.22
   185.5 1098.08   187.3 1097.87   194.9 1096.96   202.3 1097.91   204.3 1098.17
   223.1 1104.18   232.5 1106.13     242 1107.32   260.9 1109.28   279.8 1111.63
   289.2 1112.64   308.1 1114.33   336.4 1116.24   345.9 1117.18   355.4 1119.31
   364.8 1122.76   374.2 1125.85   383.7 1127.91   430.9 1136.02   459.3 1140.69
#Mann= 3 , 0 , 0
       0      .1       0   187.3    .045       0   202.3      .1       0
Bank Sta=187.3,202.3
XS Rating Curve= 0 ,0
Exp/Cntr=0.3,0.1

Type RM Length L Ch R = 1 ,3860.4  ,257.2,232.9,208.4
XS GIS Cut Line= 4
     1827188.779       314398.39     1827187.694       314475.43
       1827193.3      314625.494     1827361.703      314885.043
#Sta/Elev= 30
       0 1125.24    38.5 1123.53    48.2 1122.25    57.8 1118.98    67.4 1113.68
      77 1107.68    86.4 1102.65    95.8 1099.29   105.2 1096.96   114.6 1093.79
     124 1090.22   142.8  1086.5   146.1  1086.1   152.1 1085.36   161.1 1085.98
   170.9 1088.25   180.3 1090.95   189.7 1093.13   199.1 1094.31   208.4 1094.62
   285.2 1095.22   372.2 1097.28   401.2 1097.47   430.3  1097.3   449.6 1097.73
   459.3  1099.5   468.9 1102.68   497.9 1115.94   507.6 1120.11   536.6 1130.55
#Mann= 3 , 0 , 0
       0      .1       0   146.1    .045       0   161.1      .1       0
Bank Sta=146.1,161.1
XS Rating Curve= 0 ,0
Exp/Cntr=0.3,0.1

Type RM Length L Ch R = 1 ,3627.5  ,256.8,230,199.8
XS GIS Cut Line= 4
     1826901.019      314655.031     1827037.304      314728.815
     1827106.748      314763.537     1827317.686      314887.669
#Sta/Elev= 30
       0 1168.26    29.1 1159.24    38.7 1155.85    48.4 1152.21    67.8  1144.5
   116.2 1124.58   125.9 1120.42   135.6 1115.44   145.3 1109.53   164.7 1097.48
   174.4 1090.71   184.1 1084.78   192.8 1082.37   193.8 1082.09   203.5 1083.02
  205.39 1083.88   222.9 1091.22   232.6 1091.72   291.4 1091.86   320.7 1092.45
   350.1 1093.36   359.9  1093.5   379.5 1093.51     399 1094.28   408.8 1094.88
   418.6 1095.79   428.4 1097.14   438.2 1099.95     448 1104.26   477.4 1118.08
#Mann= 3 , 0 , 0
       0      .1       0   192.8    .045       0  205.39      .1       0
Bank Sta=192.8,205.39
XS Rating Curve= 0 ,0
Exp/Cntr=0.3,0.1

Type RM Length L Ch R = 1 ,3397.5  ,63.4,66.7,70.6
XS GIS Cut Line= 6
     1826758.404      314971.848     1826939.828      314977.925
     1826967.497      314976.623     1827014.372      314946.241
     1827077.306      314890.251     1827306.473      314911.084
#Sta/Elev= 30
       0 1127.81    28.7 1121.85    38.2 1119.74    47.8 1117.28    57.3  1114.3
    76.4 1107.66   105.1 1098.09   124.2 1090.24   133.8 1087.31   143.3 1086.03
     172 1085.68   181.5 1085.37   190.8 1084.83     200 1083.99   218.5 1079.89
   227.8 1078.31   237.2 1077.74   246.5 1078.33   274.4  1085.3   283.8 1086.59
   293.2 1087.07   368.5 1089.36   464.4 1093.07   502.7 1095.55   512.3 1096.44
   521.9  1098.4   531.5 1102.07   541.1 1106.22   569.8 1117.58   579.4 1120.99
#Mann= 3 , 0 , 0
       0     .08       0   227.8    .045       0   246.5     .08       0
Bank Sta=227.8,246.5
XS Rating Curve= 0 ,0
Exp/Cntr=0.3,0.1

Type RM Length L Ch R = 1 ,3330.8  ,152.7,179.8,209.3
XS GIS Cut Line= 6
     1826749.748      315027.889     1826934.402      315045.199
     1826962.072      315043.897     1827008.947      315013.515
     1827071.881      314957.525     1827301.047      314978.359
#Sta/Elev= 30
       0 1117.87     9.8  1115.6    19.5 1112.39    48.8 1097.61    97.6 1084.42
   107.4 1082.46   117.1 1081.35   136.7 1080.88   203.9 1082.71   213.2 1082.34
     237 1077.58   241.1 1077.06     252 1077.35   259.7  1078.7     269 1082.16
   278.4 1084.58   287.7 1085.88   297.1 1085.71   315.8 1084.18   325.2 1084.26
   353.3 1087.01   410.8 1089.02   449.1 1091.62   468.3 1094.17   487.5 1097.94
   497.1 1101.14   506.7 1105.64   525.8 1115.96   535.4 1120.31   583.4 1136.21
#Mann= 3 , 0 , 0
       0     .07       0     237    .045       0     252      .1       0
Bank Sta=237,252
XS Rating Curve= 0 ,0
Exp/Cntr=0.3,0.1

Type RM Length L Ch R = 1 ,3151    ,463.5,464.9,465.7
XS GIS Cut Line= 4
     1826731.733      315055.789     1826924.106      315171.075
     1827001.146      315224.243     1827124.844      315307.794
#Sta/Elev= 30
       0 1114.38     9.8 1111.28      39 1101.05    48.8  1097.5      78  1085.8
    87.8 1082.88    97.5  1081.3   107.3 1080.38   126.8 1078.83   146.3 1077.71
   233.6 1074.26   261.7 1073.27   271.1 1073.04   275.3 1073.03   280.4 1073.02
   289.8 1074.15   290.3 1074.37   299.2 1078.22   308.5 1084.12   317.9 1089.38
   327.2 1093.64   336.5 1098.05   345.9 1102.71   373.8 1117.31   383.2 1121.89
   392.5 1125.83   401.8 1129.08   411.2 1131.66   429.8 1136.34   467.2 1145.11
#Mann= 3 , 0 , 0
       0     .06       0   275.3    .045       0   290.3      .1       0
Bank Sta=275.3,290.3
XS Rating Curve= 0 ,0
Exp/Cntr=0.3,0.1

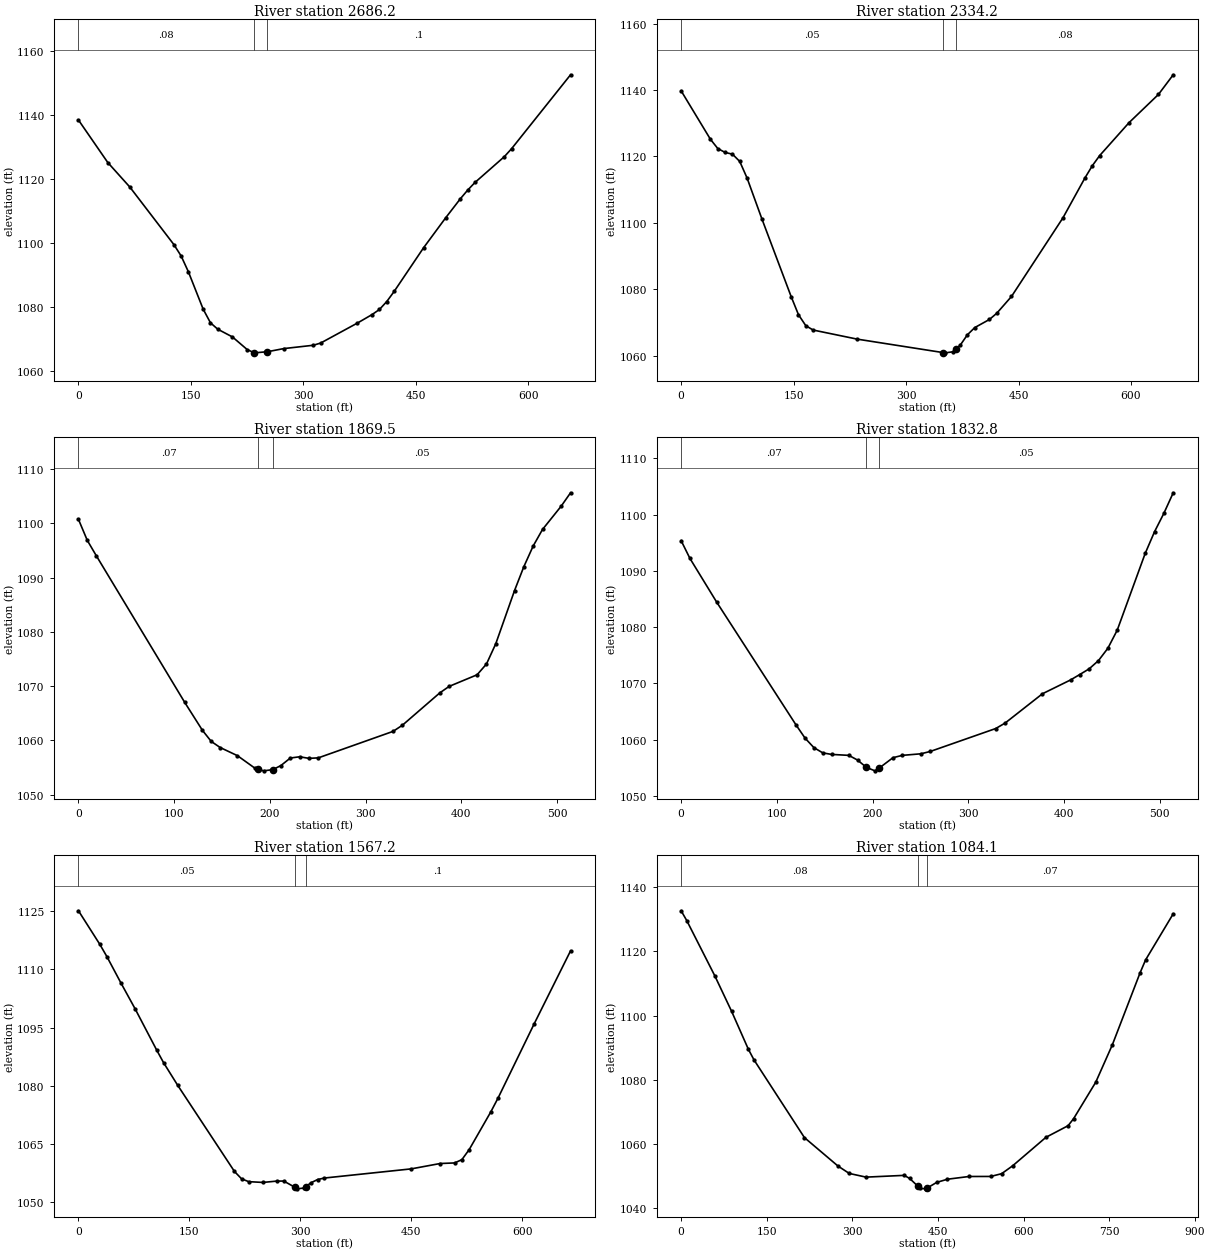
Type RM Length L Ch R = 1 ,2686.2  ,352,352,351.9
XS GIS Cut Line= 3
     1826395.677      315294.773     1826590.213      315442.928
     1826919.766      315689.738
#Sta/Elev= 30
       0 1138.49    39.1  1125.2    68.5 1117.53   127.2 1099.55   136.9 1095.99
   146.7 1090.97   166.3 1079.34   176.1 1075.05   185.8 1073.06   205.4 1070.64
     225  1066.7  233.86 1065.74   234.8 1065.67     252 1066.02   273.9    1067
   313.2 1068.04     323 1068.73     372 1074.98   391.6 1077.64   401.4 1079.23
   411.2 1081.72     421 1084.86   460.2 1098.51   489.6 1107.86   509.2 1113.82
     519 1116.54   528.8 1118.95     568 1127.03   577.8 1129.56   656.3 1152.64
#Mann= 3 , 0 , 0
       0     .08       0  233.86    .045       0     252      .1       0
Bank Sta=233.86,252
XS Rating Curve= 0 ,0
Exp/Cntr=0.3,0.1

Type RM Length L Ch R = 1 ,2334.2  ,460.4,464.7,467.1
XS GIS Cut Line= 3
      1826215.99       315536.96     1826410.526      315685.116
     1826740.078      315931.926
#Sta/Elev= 30
       0 1139.77    39.1 1125.16    48.9 1122.38    58.7  1121.2    68.5 1120.68
    78.2 1118.48      88 1113.46   107.6 1101.24   146.7 1077.78   156.5  1072.3
   166.3 1068.98   176.1 1067.68   234.8 1064.94  349.24 1060.89   352.4 1060.81
   362.2 1061.12   366.7 1062.01     372 1063.05   381.8 1066.25   391.6 1068.42
   411.2 1070.87     421 1072.75   440.6  1077.8   509.2 1101.49   538.6 1113.54
   548.4  1117.2   558.2 1120.26   597.4 1130.19   636.6 1138.69   656.3 1144.61
#Mann= 3 , 0 , 0
       0     .05       0  349.24    .045       0   366.7     .08       0
Bank Sta=349.24,366.7
XS Rating Curve= 0 ,0
Exp/Cntr=0.3,0.1

Type RM Length L Ch R = 1 ,1869.5  ,36.8,36.7,36.4
XS GIS Cut Line= 4
      1826009.27      315825.657     1826118.992      315924.963
     1826164.155      315969.635     1826391.909      316168.713
#Sta/Elev= 30
       0 1100.72     9.2 1096.86    18.5 1094.06     111    1067   129.5 1061.85
   138.7 1059.81     148 1058.69   166.1 1057.18   184.3 1054.88     188 1054.68
   193.4 1054.39     203 1054.61   211.5 1055.37   221.3 1056.75     231 1056.98
   240.8 1056.69   250.5 1056.78   328.6 1061.66   338.4  1062.8   377.4 1068.75
   387.2 1069.95   416.4 1072.09   426.2 1074.08   435.9 1077.81   455.5 1087.61
   465.2    1092     475 1095.83   484.7 1098.86   504.2 1103.15     514 1105.62
#Mann= 3 , 0 , 0
       0     .07       0     188    .045       0     203     .05       0
Bank Sta=188,203
XS Rating Curve= 0 ,0
Exp/Cntr=0.3,0.1

Type RM Length L Ch R = 1 ,1832.8  ,261.3,265.6,269.9
XS GIS Cut Line= 4
     1825983.576      315851.351     1826093.298      315950.657
     1826138.461      315995.329     1826366.215      316194.407
#Sta/Elev= 30
       0 1095.37     9.2 1092.21      37 1084.48   120.2 1062.57   129.5 1060.26
   138.7 1058.58     148 1057.65   157.1 1057.38   175.2 1057.21   184.3 1056.37
   193.4 1055.09   202.4 1054.46   207.1 1054.98   221.3  1056.8     231 1057.21
   250.5 1057.49   260.3 1057.91   328.6 1061.98   338.4 1062.95   377.4 1068.16
   406.7 1070.61   416.4 1071.58   426.2 1072.59   435.9 1074.05   445.7 1076.24
   455.5 1079.46   484.7  1093.1   494.5 1096.97   504.2 1100.22     514 1103.88
#Mann= 3 , 0 , 0
       0     .07       0   193.4    .045       0   207.1     .05       0
Bank Sta=193.4,207.1
XS Rating Curve= 0 ,0
Exp/Cntr=0.3,0.1

Type RM Length L Ch R = 1 ,1567.2  ,489.3,483.1,476.2
XS GIS Cut Line= 4
      1825740.11       315893.37     1825899.616      316109.298
     1825936.508      316161.382     1826126.395      316434.819
#Sta/Elev= 30
       0 1125.06    28.8 1116.44    38.4 1113.27    57.5 1106.44    76.7 1099.77
   105.5 1089.28     115 1085.96   134.2  1080.1   210.9 1057.93   220.5 1056.04
   230.1 1055.31   249.3 1055.11   268.4 1055.46   277.6 1055.46   292.5 1053.87
   295.8 1053.46   304.9 1053.68   307.5 1054.05     314 1054.99   323.2 1055.85
   332.3 1056.24   449.8  1058.6   488.9 1059.98   508.5 1060.13   518.3 1060.98
   528.1 1063.54   557.5 1073.31   567.3 1076.88   616.2 1096.02   665.2 1114.74
#Mann= 3 , 0 , 0
       0     .05       0   292.5    .045       0   307.5      .1       0
Bank Sta=292.5,307.5
XS Rating Curve= 0 ,0
Exp/Cntr=0.3,0.1

Type RM Length L Ch R = 1 ,1084.1  ,351.1,350.4,345.3
XS GIS Cut Line= 4
     1825320.724      316140.288     1825562.911      316383.778
     1825732.182      316504.871     1825997.807      316665.028
#Sta/Elev= 30
       0 1132.67     9.8 1129.63    58.9 1112.42    88.3 1101.36   117.8 1089.48
   127.6 1086.19   215.9 1061.97   274.7  1053.1   294.4  1050.8   323.8 1049.65
   390.7  1050.2   400.2 1049.23   414.7  1046.8   419.1 1046.14   428.6    1046
   429.7 1046.13   447.5 1048.01   466.4    1049   504.2 1049.85   542.1 1049.86
   561.2 1050.72   580.6 1053.19   638.8 1062.06   677.6 1065.68   687.2 1067.86
     726 1079.23   755.1  1090.9   803.6 1113.31   813.3 1117.36   861.7 1131.73
#Mann= 3 , 0 , 0
       0     .08       0   414.7    .045       0   429.7     .07       0
Bank Sta=414.7,429.7
XS Rating Curve= 0 ,0
Exp/Cntr=0.3,0.1

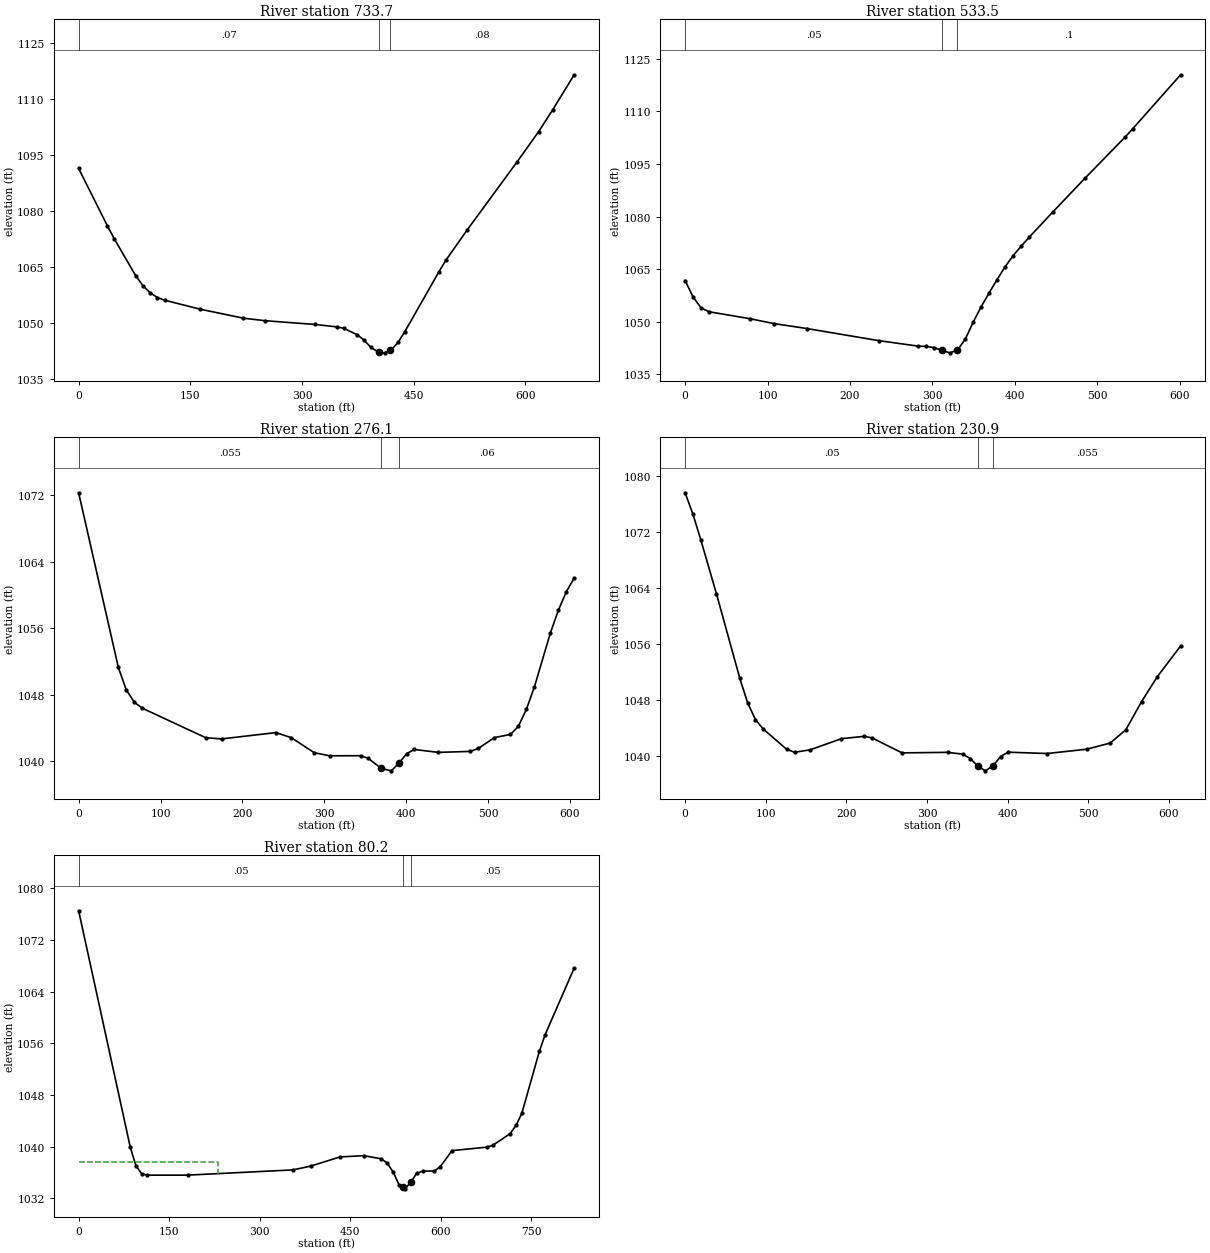
Type RM Length L Ch R = 1 ,733.7   ,195.4,200.2,203.5
XS GIS Cut Line= 4
     1825050.585      316476.486      1825374.37      316624.923
     1825470.724        316693.5     1825610.778      316823.451
#Sta/Elev= 30
       0 1091.32    38.5 1076.02    48.1  1072.4      77 1062.52    86.6  1059.9
    96.3 1058.02   105.9 1056.79   115.5 1056.07   163.6 1053.65   221.4 1051.26
   250.3 1050.59   317.7 1049.58   346.6 1048.94   356.2 1048.54   374.4  1046.8
   383.5 1045.35   392.6 1043.43     403 1042.14   410.8 1041.99     418 1042.62
   419.9 1042.78     429  1044.8   438.1 1047.66     484 1063.74   493.6 1066.89
   522.2 1074.98   589.1 1093.16   617.8 1101.18   636.8 1107.07   665.5 1116.39
#Mann= 3 , 0 , 0
       0     .07       0     403    .045       0     418     .08       0
Bank Sta=403,418
XS Rating Curve= 0 ,0
Exp/Cntr=0.3,0.1

Type RM Length L Ch R = 1 ,533.5   ,247.5,257.4,267.6
XS GIS Cut Line= 4
     1825087.651       316603.83     1825234.786      316734.038
      1825355.88      316856.434      1825512.13      317028.309
#Sta/Elev= 29
       0 1061.72     9.8 1056.96    19.6 1053.84    29.5 1052.78    78.6 1050.82
   108.1 1049.41   147.4 1048.02   234.7 1044.56   282.6 1042.99   292.1 1042.89
   301.7 1042.57   311.3 1041.81   320.8 1041.07   330.1 1041.83   330.4 1041.85
     340  1045.1   349.5 1049.91   359.1 1054.26   368.6 1058.16   378.3 1061.98
     388 1065.63   397.7  1068.8   407.4 1071.49     417 1074.02   446.1 1081.34
   484.8  1090.9   533.2 1102.59   542.9 1105.09   600.9 1120.47
#Mann= 3 , 0 , 0
       0     .05       0   311.3    .045       0   330.1      .1       0
Bank Sta=311.3,330.1
XS Rating Curve= 0 ,0
Exp/Cntr=0.3,0.1

Type RM Length L Ch R = 1 ,276.1   ,44.8,45.3,45.3
XS GIS Cut Line= 6
     1825044.779      316650.928     1825109.294      316833.784
      1825147.89      316988.862     1825166.119      317041.987
     1825185.381      317147.926     1825215.873      317230.008
#Sta/Elev= 30
       0  1072.3    48.5 1051.29    58.2 1048.58    67.9 1047.12    77.6 1046.39
   155.1 1042.84   174.5 1042.69   240.9 1043.45   259.7 1042.84   287.9 1041.02
   306.7 1040.66   344.3 1040.67   353.7 1040.35   369.5 1039.14   381.8 1038.85
   391.2 1039.78   400.5 1040.91   409.9 1041.42   439.2 1041.07   478.4 1041.19
   488.2 1041.56   507.8 1042.85   527.3 1043.23     537 1044.21   546.7 1046.24
   556.5 1048.93   575.9 1055.39   585.7 1058.14   595.4 1060.38   605.1 1062.04
#Mann= 3 , 0 , 0
       0    .055       0   369.5    .045       0   391.2     .06       0
Bank Sta=369.5,391.2
XS Rating Curve= 0 ,0
Exp/Cntr=0.3,0.1

Type RM Length L Ch R = 1 ,230.9   ,160.9,150.7,140.9
XS GIS Cut Line= 6
     1825006.932      316678.012     1825071.447      316860.867
     1825110.043      317015.946     1825128.272      317069.071
     1825147.533      317175.009     1825191.099      317261.663
#Sta/Elev= 30
       0 1077.64     9.7 1074.58    19.4 1070.93    38.8  1063.2    67.9 1051.04
    77.6 1047.53    87.3 1045.14      97 1043.79     126 1040.89   135.7 1040.47
   155.1 1040.82   193.9 1042.42   222.1 1042.75   231.5 1042.54   269.1 1040.38
   325.5 1040.46   344.3  1040.2   353.7 1039.57   363.1 1038.47   372.4 1037.81
   381.8 1038.53   391.2 1039.86   400.5 1040.48     449 1040.29     498 1040.91
   527.2 1041.79   546.6  1043.7     566 1047.72   585.4 1051.27   614.5  1055.7
#Mann= 3 , 0 , 0
       0     .05       0   363.1    .045       0   381.8    .055       0
#XS Ineff= 2 , 0
          240.01 1042.05
Permanent Ineff=
       F       F
Bank Sta=363.1,381.8
XS Rating Curve= 0 ,0
Exp/Cntr=0.3,0.1

Type RM Length L Ch R = 1 ,80.2    ,66,80.2,94.3
XS GIS Cut Line= 5
     1824725.086      316699.714     1824843.359      316905.877
     1824994.027      317110.998     1825070.416      317186.692
     1825233.984      317336.649
#Sta/Elev= 30
       0  1076.5    85.6 1039.93    95.1 1037.04   104.6  1035.8   114.1  1035.6
   180.6  1035.6   355.2 1036.41   384.5 1036.99   433.5 1038.42   472.6 1038.61
     502 1038.12   511.7 1037.46   521.5 1036.08   531.3 1034.09   537.8 1033.69
   541.1 1033.48   550.8 1034.52   560.6 1035.88   570.4 1036.22     590 1036.25
   599.7 1036.92     619 1039.39   676.9 1039.93   686.6 1040.21   715.5 1042.02
   725.2 1043.29   734.8 1045.16   763.8 1054.73   773.4 1057.32   821.6 1067.64
#Mann= 3 , 0 , 0
       0     .05       0   537.8    .045       0   550.8     .05       0
#XS Ineff= 2 , 0
          231.32 1037.63
Permanent Ineff=
       F       F
Bank Sta=537.8,550.8
XS Rating Curve= 0 ,0
Exp/Cntr=0.3,0.1

Chan Stop Cuts=-1
Use User Specified Reach Order=0
Composite Channel Slope=5